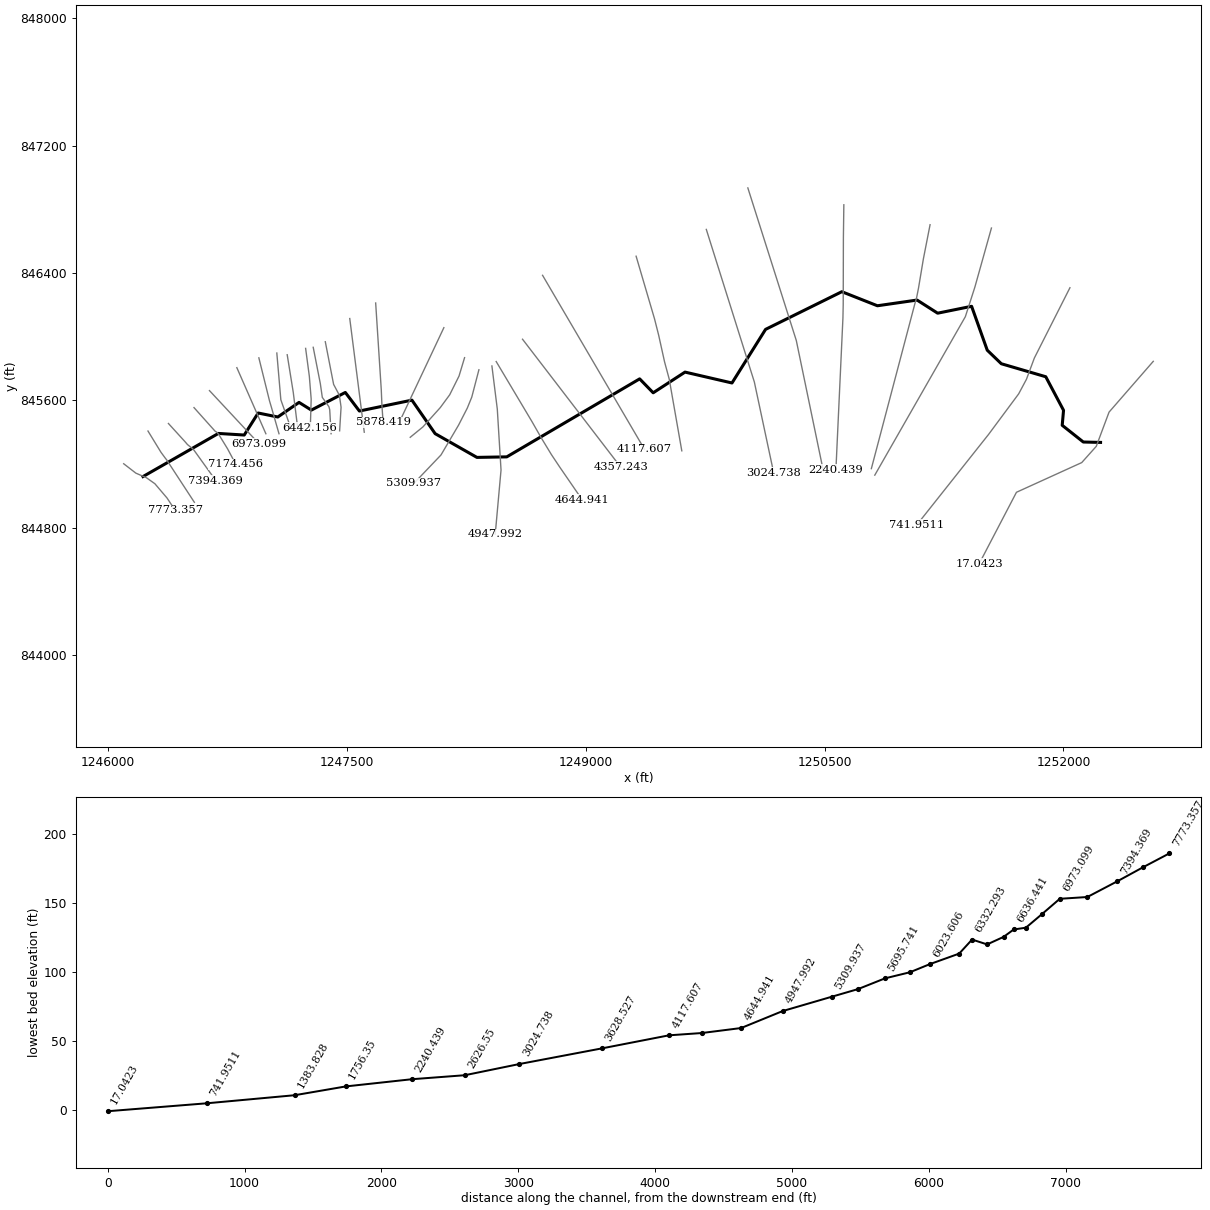
--- 116_ras.prj (project) ---

Proj Title=116
Current Plan=p01
Default Exp/Contr=0.3,0.1
English Units
Geom File=g01
Flow File=f01
Plan File=p01
Y Axis Title=Elevation
X Axis Title(PF)=Main Channel Distance
X Axis Title(XS)=Station
BEGIN DESCRIPTION:
RFD model 116 exported to HEC-RAS
END DESCRIPTION:

--- 116_ras.p01 (plan) ---

Plan Title=Plan 01
Program Version=4.10
Short Identifier=Plan 01
Geom File=g01
Flow File=f01
Subcritical Flow
Calc Critical at every XS
Secant Critical Depth

--- 116_ras.f01 (steady flow) ---

Flow Title=Flow 01
Program Version=5.01
Number of Profiles= 5
Profile Names=10yr,25yr,50yr,100yr,500yr
River Rch & RM=116,29,7773.357
  399.14  728.37 1061.93 1478.27 2814.74
River Rch & RM=116,29,7583.863
  510.51  936.66 1372.68 1921.53 3713.84
River Rch & RM=116,29,7394.369
  515.28  945.61 1386.06 1940.68 3752.97
River Rch & RM=116,29,7174.456
  523.04  960.15 1407.82 1971.81 3816.64
River Rch & RM=116,29,6973.099
  540.32  992.59 1456.37 2041.32 3958.98
River Rch & RM=116,29,6725.326
  548.06 1007.13 1478.15  2072.5 4022.93
River Rch & RM=116,29,6636.441
  555.21 1020.54 1498.25  2101.3 4082.05
River Rch & RM=116,29,6562.621
  561.75 1032.84 1516.67 2127.71  4136.3
River Rch & RM=116,29,6332.293
  570.08 1048.49 1540.13 2161.34 4205.43
River Rch & RM=116,29,6238.284
  761.33 1409.15 2082.51  2941.7 5825.29
River Rch & RM=116,29,6023.606
  778.43 1441.49 2131.31 3012.14 5972.82
River Rch & RM=116,29,5878.419
  783.73 1451.53 2146.45 3034.01 6018.68
River Rch & RM=116,29,5695.741
   785.5 1454.87  2151.5 3041.31 6033.97
River Rch & RM=116,29,5499.431
  795.51 1473.83 2180.11 3082.64 6120.67
River Rch & RM=116,29,5309.937
  799.04 1480.52 2190.21 3097.23  6151.3
River Rch & RM=116,29,4947.992
  876.08 1626.53 2410.87 3416.38 6823.21
River Rch & RM=116,29,4644.941
 1676.76 3157.71 4744.66 6823.1214175.23
River Rch & RM=116,29,4357.243
 1693.46 3189.86 4793.97 6895.5814334.39
River Rch & RM=116,29,4117.607
 1715.34 3231.98 4858.59 6990.5614543.17
River Rch & RM=116,29,3628.527
 1730.31 3260.81 4902.81 7055.5714686.17
River Rch & RM=116,29,3024.738
 1750.45  3299.6 4962.35 7143.1214878.86
River Rch & RM=116,29, 2626.55
 1756.78 3311.79 4981.06 7170.6414939.46
River Rch & RM=116,29,2240.439
 2505.11  4759.4 7211.8710465.8522279.87
River Rch & RM=116,29, 1756.35
 2577.38 4899.76 7428.9910787.8923005.14
River Rch & RM=116,29,1383.828
  2717.2 5171.56 7849.79 11412.624415.56
River Rch & RM=116,29,741.9511
 2765.46 5265.45 7995.2611628.7324904.55
River Rch & RM=116,29, 17.0423
 2775.11 5284.22 8024.3611671.9725002.45
Boundary for River Rch & Prof#=116,29,1
Up Type= 0
Dn Type= 2
Boundary for River Rch & Prof#=116,29,2
Up Type= 0
Dn Type= 2
Boundary for River Rch & Prof#=116,29,2
Up Type= 0
Dn Type= 2
Boundary for River Rch & Prof#=116,29,2
Up Type= 0
Dn Type= 2
Boundary for River Rch & Prof#=116,29,2
Up Type= 0
Dn Type= 2

--- 116_ras.g01 (geometry) ---

Geom Title=116
Program Version=4.10

River Reach=116,29
Reach XY= 30
1246218.73079741845120.8564413241246692.06399969845391.689680763
1246854.56395167845381.6896789631246942.06393003 845520.02296888
1247065.39722642845495.022972655 1247198.7305233845586.689608345
1247276.23049911845538.3562870041247489.56377305 845649.18958134
1247577.89707703845532.5229465531247907.89698213845600.856250056
1248053.67082461 845390.411409461248316.17074316845241.244779163
1248503.67068819845244.5781060311249338.26530668845734.519386849
1249423.26527915845647.0194102131249623.26522423845777.019365927
1249918.26513561845708.6860441451250129.09841691846045.352605156
1250608.26494983846282.0191878821250831.59821498846193.685874078
1251080.76480953846229.5191895241251209.93143585846147.019210103
1251423.26470781846190.3525243871251521.59800417845914.519269648
1251609.93130907845829.5192921821251889.09789136845747.852641444
1252000.76451904845537.0193671221251992.43118539845442.852728545
 1252124.9311434845337.8527556561252233.26444485845335.352753206

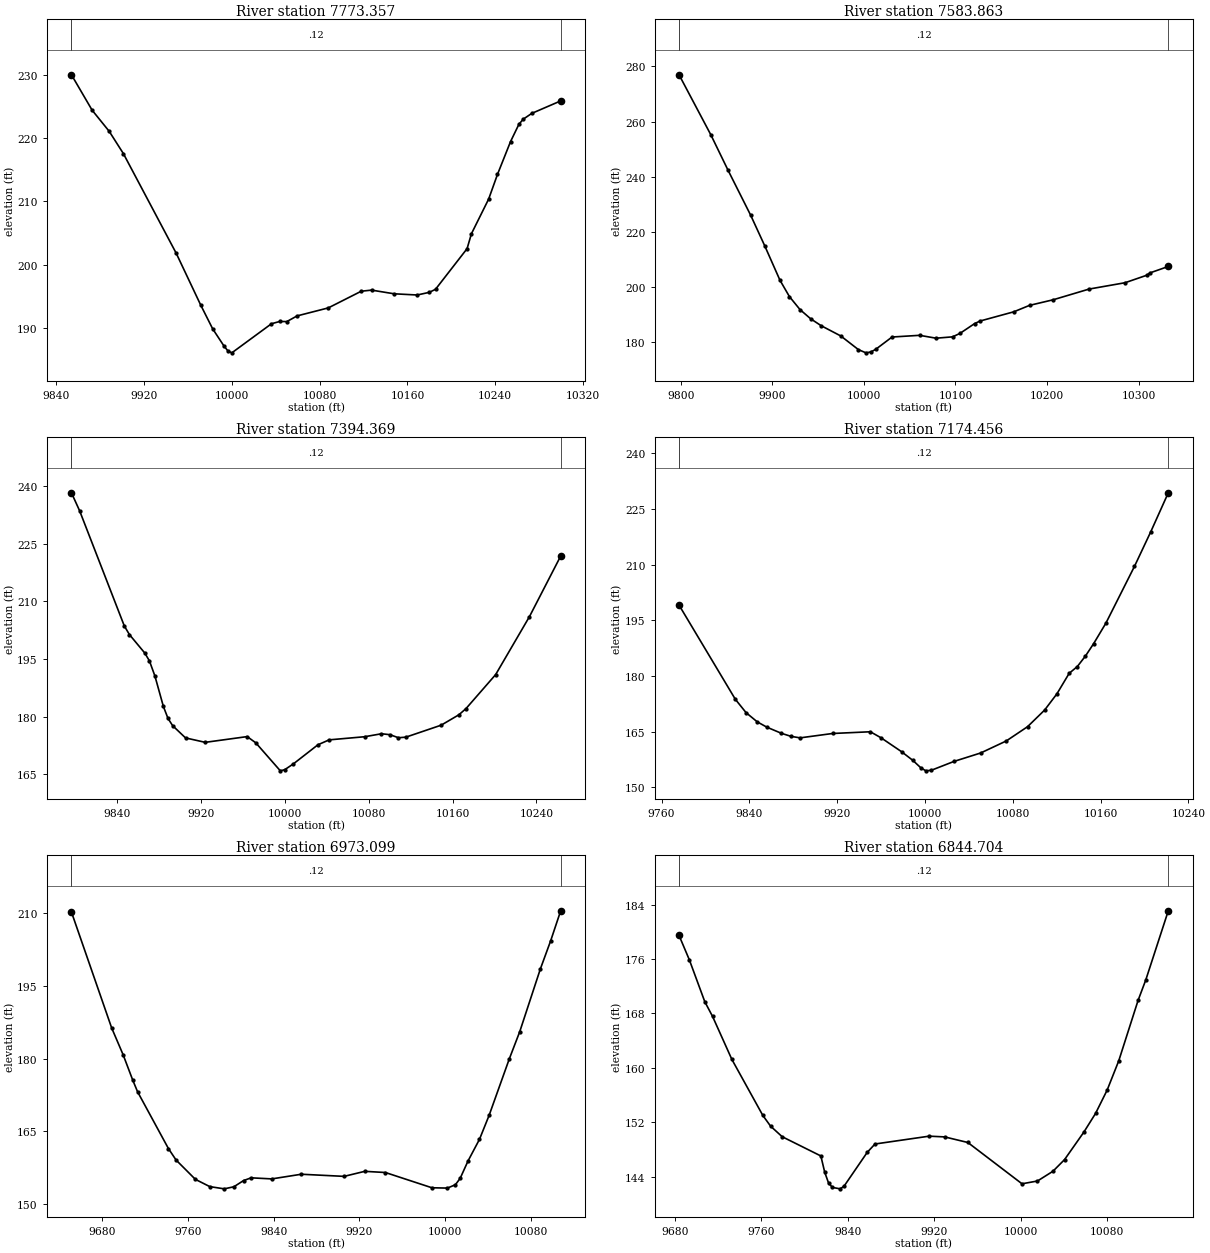
Type RM Length L Ch R = 1 ,7773.357,189.493800,189.493800,189.493800
XS GIS Cut Line= 6
 1246097.4872083845201.3570805321246173.92689327845142.332827439
1246239.38702974845114.0775901581246293.10603394845076.079526658
1246369.48103882844986.4060889481246421.31969069844908.018187162
#Sta/Elev= 30
9853.662229.97119872.532224.3807  9888.1221.04549900.992217.53929949.218201.7945
9971.466  193.659982.419189.88099992.912187.12249996.409186.38179999.891186.0941
10036.03190.684910043.61191.047510049.99191.025110059.41191.924310087.79193.1834
10117.87 195.81610127.29195.992210147.87195.409810168.83195.221610179.92195.6405
10185.59196.124110214.36202.535810218.29204.878310234.02210.358610242.05214.2423
10253.95219.420510261.56222.143410265.49222.958610273.36223.882310299.69 225.848
#Mann= 3 , 0 , 0
9853.662    0.12       09853.662    0.12       010299.69    0.12       0
#XS Ineff= 2 , 0
       0                               0
Bank Sta=9853.662,10299.69
Exp/Cntr=0.3,0.1

Type RM Length L Ch R = 1 ,7583.863,189.493800,189.493800,189.493800
XS GIS Cut Line= 6
1246250.01768176845406.7854690991246332.01364075845272.812740241
1246357.91900237845237.6741977961246368.79134729845223.806819128
 1246378.3842931  845208.74259381246541.24110709  844959.3497077
#Sta/Elev= 30
9798.271 276.9459832.978255.18969851.833242.3004 9876.47226.03379891.856214.9259
9908.396202.51289918.782196.55289930.321191.85469941.861188.5448  9953.4186.0146
9974.861182.29179994.045177.352310002.32176.182210007.66176.503410012.99177.4646
10030.79181.916210060.86182.529810078.86181.487810096.86 181.97810104.88183.2204
10120.86186.768110126.87187.711310163.66  191.0510180.87193.383910206.76195.4208
10245.94199.296910285.13201.586810308.64204.279410312.55205.177110332.34207.4829
#Mann= 3 , 0 , 0
9798.271    0.12       09798.271    0.12       010332.34    0.12       0
#XS Ineff= 2 , 0
       0                10046.86       0
Bank Sta=9798.271,10332.34
Exp/Cntr=0.3,0.1

Type RM Length L Ch R = 1 ,7394.369,219.913300,219.913300,219.913300
XS GIS Cut Line= 6
1246378.48069043845454.1413743681246485.24716438845337.049645047
1246497.71735649845322.2689889681246528.70664573845297.071733868
1246539.03444048845286.535495808 1246675.7897182845096.068457701
#Sta/Elev= 30
9796.152238.28119803.983233.57739846.631  203.61  9851.5201.37539866.142196.5777
9870.582194.53749875.847190.57869883.902182.67579888.342179.53649892.782177.6576
9905.063174.48239923.861173.32879963.893174.8252  9972.1173.20919995.544165.9127
9999.785166.220610008.02167.728410031.42172.693710042.13173.975210075.94174.7872
10092.08175.561710100.16175.325210108.23174.533110115.28174.672810149.07177.7988
10165.97180.500410172.81 182.12710201.07190.965310233.36206.063910263.14221.8138
#Mann= 3 , 0 , 0
9796.152    0.12       09796.152    0.12       010263.14    0.12       0
#XS Ineff= 2 , 0
       09961.824                       0
Bank Sta=9796.152,10263.14
Exp/Cntr=0.3,0.1

Type RM Length L Ch R = 1 ,7174.456,201.356900,201.356900,201.356900
XS GIS Cut Line= 6
 1246539.0709682845553.967763257 1246671.2900607845406.142781422
1246683.63927083845398.147186637 1246694.5883748845385.334091097
1246749.57444043845295.7212354791246801.65777376845198.064985479
#Sta/Elev= 30
9775.981199.08849827.254173.72829837.097170.10779847.249167.64579856.052166.2049
9869.257164.56139878.061163.73359886.309 163.3379915.837164.51289950.285164.9792
9960.128163.3329 9978.68159.61759989.021157.26219996.343 155.24910000.91 154.453
10005.88154.610810026.55156.998710050.83 159.26810074.11162.5018 10093.5166.3447
10109.02170.812610120.26175.196810131.41180.714610138.85182.550610146.29185.3912
10153.72188.718310164.88194.233410190.91209.524410205.78218.859710221.73229.3485
#Mann= 3 , 0 , 0
9775.981    0.12       09775.981    0.12       010221.73    0.12       0
#XS Ineff= 2 , 0
       09945.925                       0
Bank Sta=9775.981,10221.73
Exp/Cntr=0.3,0.1

Type RM Length L Ch R = 1 ,6973.099,128.395400,128.395400,128.395400
XS GIS Cut Line= 2
1246636.29319043 845660.738596591246947.05707932845327.405263257
#Sta/Elev= 30
9651.685 210.2799689.142186.36489699.835180.82149708.806175.58069713.292173.1849
9742.066161.45259749.175159.09599767.117155.11779780.574153.6139 9794.03 153.157
9803.001153.58379811.972154.86059819.045155.4301 9838.29155.20779865.798156.1692
9905.648  155.739924.893156.76839944.138156.52579987.439153.379610001.87153.3115
10009.33154.005710013.82155.342310021.12158.919510031.76163.372110040.73168.3152
10059.61180.016110069.23185.561510088.47198.5263 10098.1204.357410107.41 210.536
#Mann= 3 , 0 , 0
9651.685    0.12       09651.685    0.12       010107.41    0.12       0
#XS Ineff= 2 , 0
       09933.366                       0
Bank Sta=9651.685,10107.41
Exp/Cntr=0.3,0.1

Type RM Length L Ch R = 1 ,6844.704,119.377400,119.377400,119.377400
XS GIS Cut Line= 2
1246808.16819043845804.8358188131246990.45985709845389.905263257
#Sta/Elev= 30
9683.674179.4536 9693.19175.87779707.524169.70899714.691167.55579732.609161.2231
9761.277 152.9939768.444151.41769779.194149.86239815.029147.03199818.613144.6394
9822.196143.0418 9825.78142.40369832.947142.1976 9836.53142.58969858.031147.5717
9865.198148.78999915.367149.94189929.701149.83429951.202149.011110001.37142.9398
 10015.7143.349910030.04144.784210040.79146.498610058.71150.548510069.46153.2748
10080.21156.705310090.96161.011310108.88169.898510116.04172.919510136.88183.0806
#Mann= 3 , 0 , 0
9683.674    0.12       09683.674    0.12       010136.88    0.12       0
#XS Ineff= 2 , 0
       09942.477                       0
Bank Sta=9683.674,10136.88
Exp/Cntr=0.3,0.1

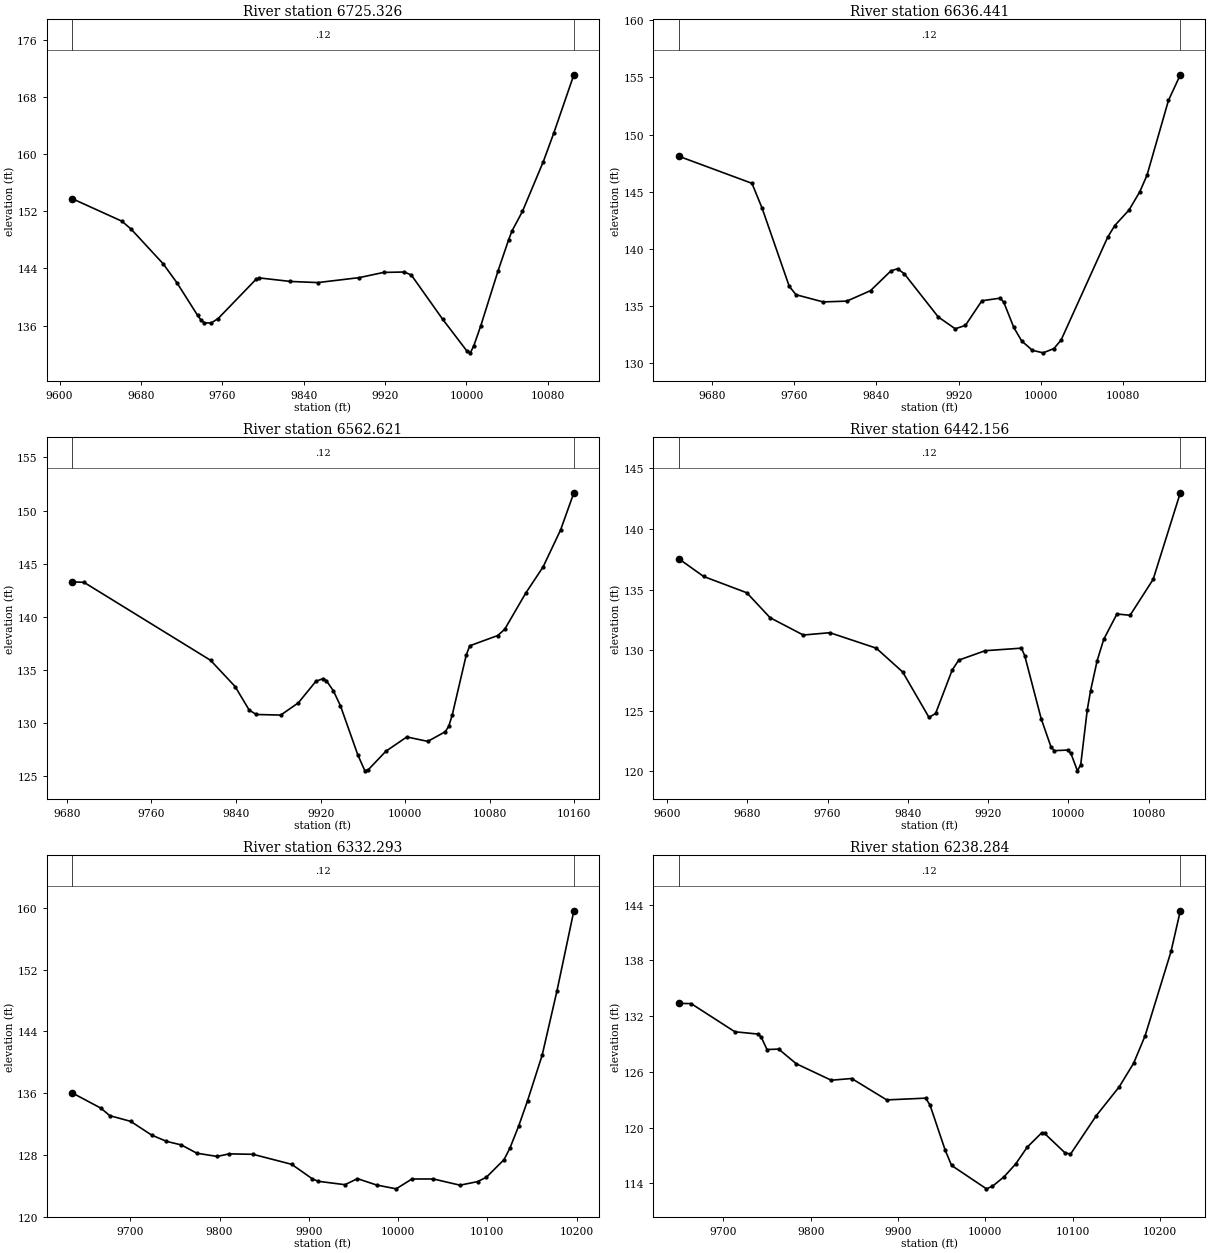
Type RM Length L Ch R = 1 ,6725.326,88.885000,88.885000,88.885000
XS GIS Cut Line= 5
1246946.44835848845866.5966262071247013.36753058845596.211124241
1247025.24047309845556.2918784171247050.53176916 845467.77234222
1247072.90483877845389.952969745
#Sta/Elev= 30
9612.341 153.7619661.281 150.6029670.377149.49499701.839144.64639715.359142.0005
9735.637137.44249739.017136.77379742.397136.37559749.157136.36539755.916136.9809
9793.094142.46079796.474142.66319826.893 142.1719853.931 142.0139894.535142.7034
9918.495143.43329939.012143.49199945.836143.06319976.545136.895410000.43132.4385
10003.84132.182710007.25 133.18910014.08135.976410031.14143.687810041.38147.9739
 10044.8149.252910055.04151.976210075.52 158.93110085.76162.902410105.56171.0859
#Mann= 3 , 0 , 0
9612.341    0.12       09612.341    0.12       010105.56    0.12       0
#XS Ineff= 2 , 0
       09898.672                       0
Bank Sta=9612.341,10105.56
Exp/Cntr=0.3,0.1

Type RM Length L Ch R = 1 ,6636.441,73.820200,73.820200,73.820200
XS GIS Cut Line= 3
 1247059.2864486845896.7516330331247084.57774472845602.983501941
1247148.77872699845421.080718741
#Sta/Elev= 30
9647.627148.1067 9718.99145.72739728.869143.55129755.213136.71979761.799135.9784
9788.143135.34699811.194135.41699834.244136.33419854.002 138.0579860.588138.2561
9867.174 137.7999900.104 134.0289916.569132.99749926.448133.28849942.481135.4491
9960.333135.67769963.812  135.319973.512 133.1129981.208131.92499991.645131.1068
10002.08130.890110012.52131.266210019.48132.009510064.71140.997710071.67142.0339
10085.58143.397610096.02144.997210102.98146.435510123.85152.986310135.38155.2287
#Mann= 3 , 0 , 0
9647.627    0.12       09647.627    0.12       010135.38    0.12       0
#XS Ineff= 2 , 0
       09949.522                       0
Bank Sta=9647.627,10135.38
Exp/Cntr=0.3,0.1

Type RM Length L Ch R = 1 ,6562.621,120.465200,120.465200,120.465200
XS GIS Cut Line= 3
1247124.46017304845886.0514693261247162.39711714 845650.64786756
1247191.57938182 845416.21700795
#Sta/Elev= 30
9684.933143.30639696.266143.2509  9815.9135.92429839.162133.45619852.455131.2475
9859.101130.82559882.363130.77019898.979131.92089915.595133.94719922.241134.1955
9925.553133.99919932.165133.04629938.778131.65169955.308127.00959961.921125.5253
9965.227125.63789981.758127.367110001.59128.712910021.43128.296210037.96129.2028
10041.27129.719410044.57130.7846 10057.8136.411310061.11 137.28710087.55138.2486
10094.17138.8336   10114 142.22810130.53144.710610147.07148.184610159.61151.6776
#Mann= 3 , 0 , 0
9684.933    0.12       09684.933    0.12       010159.61    0.12       0
#XS Ineff= 2 , 0
       09931.171        10017.85       0
Bank Sta=9684.933,10159.61
Exp/Cntr=0.3,0.1

Type RM Length L Ch R = 1 ,6442.156,109.862600,109.862600,109.862600
XS GIS Cut Line= 5
1247240.21648958845925.9338977041247263.56230137 845749.86756748
1247275.05316335 845607.61553587 1247270.0981648845442.448917389
1247267.57894066845428.058563292
#Sta/Elev= 30
9611.413137.55669636.454136.07989679.479 134.7359702.645132.68159735.741131.2514
9762.217 131.4439808.445130.17029834.777128.21059861.109124.45289867.692 124.789
 9884.15128.35799890.733129.18069917.065129.95939953.211130.16919956.493129.5468
9972.905124.34669982.752122.00819986.034121.71419999.164121.765210002.45121.5081
10009.01120.051510012.29120.552710018.86125.100110022.14126.6629 10028.7129.1418
10035.27130.9018 10048.4132.986210061.53132.8804 10084.5135.842710111.59 142.982
#Mann= 3 , 0 , 0
9611.413    0.12       09611.413    0.12       010111.59    0.12       0
#XS Ineff= 2 , 0
       0  9935.3                       0
Bank Sta=9611.413,10111.59
Exp/Cntr=0.3,0.1

Type RM Length L Ch R = 1 ,6332.293,94.009100,94.009100,94.009100
XS GIS Cut Line= 6
1247287.88085526 845932.74309282 1247332.6269944845704.148686126
  1247344.973746845618.2038743641247386.29319042845560.044152156
1247391.50152376845540.9469299171247400.18207934 845389.90526326
#Sta/Elev= 30
 9634.79  136.039667.024134.04649677.053133.07199700.455 132.3319723.856  130.56
9740.572129.74229757.287129.27499774.512128.20769797.405127.78499810.777 128.121
9837.522128.06299880.869126.7649 9904.07124.87929910.699124.5651 9940.53124.1254
 9954.55  124.919975.958 124.0859997.894123.588410015.61124.866910039.64124.8655
10069.43124.062910089.15 124.52310099.01125.094410118.75127.370610125.33128.8549
10135.19131.736510145.06  134.9910161.51140.920910177.92149.1604   10197159.6203
#Mann= 3 , 0 , 0
 9634.79    0.12       0 9634.79    0.12       0   10197    0.12       0
#XS Ineff= 2 , 0
       09957.809                       0
Bank Sta=9634.79,10197
Exp/Cntr=0.3,0.1

Type RM Length L Ch R = 1 ,6238.284,214.677700,214.677700,214.677700
XS GIS Cut Line= 6
 1247363.7547434845967.7618104371247415.98069045845699.887902141
1247448.79319042845638.1691521561247454.00152376845619.071929917
1247462.85569045845556.6587354841247453.74110711845408.221235484
#Sta/Elev= 30
9648.778133.36529663.196133.3467 9713.31130.31179740.038 130.0639743.379 129.741
9750.061128.40169763.425128.4468 9783.47126.87429823.562125.09559846.975125.2806
9887.126122.97459931.609123.16419936.627122.43359953.903117.59669961.334115.9187
10001.31 113.39810008.11 113.67110021.45114.6979 10034.7 116.07410047.96117.8899
10064.52 119.42910067.84119.360910090.87117.306810097.44117.122910126.97121.2741
10153.31 124.39110169.77126.926110182.94129.892210212.58138.960910223.22143.3427
#Mann= 3 , 0 , 0
9648.778    0.12       09648.778    0.12       010223.22    0.12       0
#XS Ineff= 2 , 0
       09927.254                       0
Bank Sta=9648.778,10223.22
Exp/Cntr=0.3,0.1

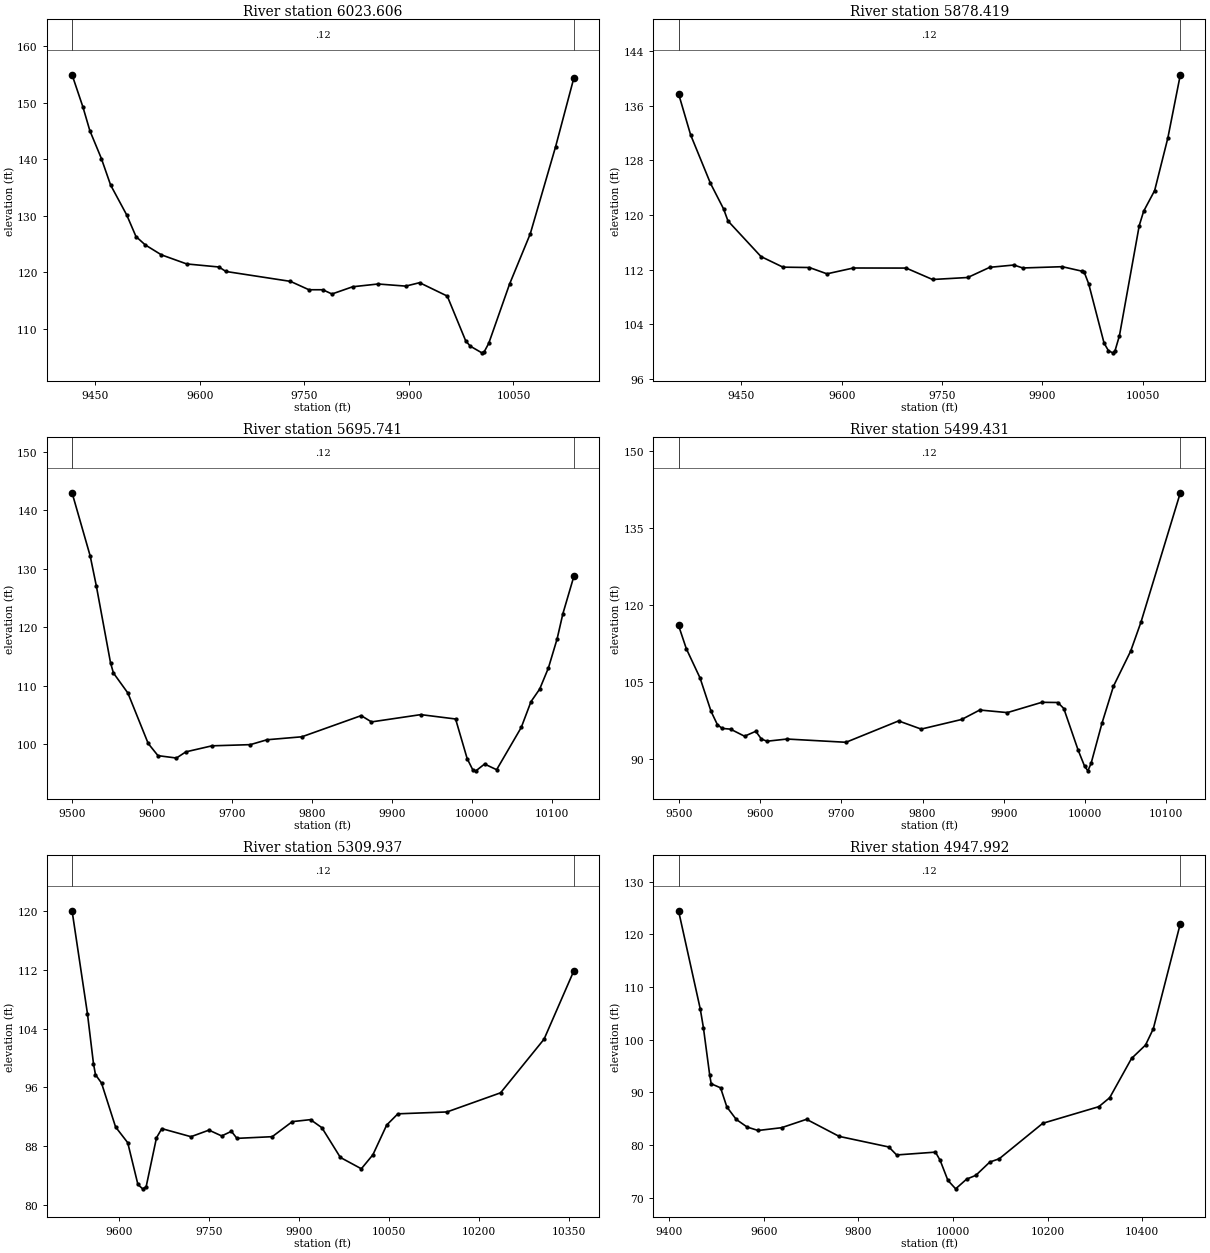
Type RM Length L Ch R = 1 ,6023.606,145.187900,145.187900,145.187900
XS GIS Cut Line= 2
1247517.36957932846113.4295688131247608.51541265845399.453874368
#Sta/Elev= 30
9416.865154.9782 9432.46149.26389442.382145.0758 9458.92140.1441 9472.15135.4529
9495.302130.14189508.532126.33649521.761124.85789544.914123.09529581.296121.4806
  9627.6120.93829637.523120.14799730.131 118.3929756.591116.91019776.436116.9096
9789.666116.15949819.433117.44089855.815117.92869895.504 117.5539915.349118.1598
9955.039115.78949981.498107.85649988.113106.914110004.65105.737510007.96105.9076
10014.57107.432410044.34117.894910074.11126.817610110.49142.268310136.63154.4152
#Mann= 3 , 0 , 0
9416.865    0.12       09416.865    0.12       010136.63    0.12       0
#XS Ineff= 2 , 0
       09873.885                       0
Bank Sta=9416.865,10136.63
Exp/Cntr=0.3,0.1

Type RM Length L Ch R = 1 ,5878.419,182.677800,182.677800,182.677800
XS GIS Cut Line= 6
1247680.12999598846211.0858188131247715.29533538845666.592862538
1247719.48185232845569.4068786121247719.56688169845567.408686928
1247719.71891168845564.0116936471247726.79307083845462.554416483
#Sta/Elev= 30
9356.097137.75029374.116131.73979403.705124.66529423.431120.89549430.006119.1394
9479.321113.93379512.198112.3817 9551.65 112.3299577.951111.40749617.403112.2591
9696.307112.24829735.759 110.5789788.362110.87039821.239112.35799857.403112.6955
9870.554112.26289929.699112.44969959.254111.79219962.538111.61849969.106109.9531
9992.093101.28889998.661100.165110005.2399.8542110008.52100.1667 10015.1102.3622
 10044.7118.464710051.27120.559910067.72123.584810087.45131.2715 10106.1 140.511
#Mann= 3 , 0 , 0
9356.097    0.12       09356.097    0.12       0 10106.1    0.12       0
#XS Ineff= 2 , 0
       09928.723                       0
Bank Sta=9356.097,10106.1
Exp/Cntr=0.3,0.1

Type RM Length L Ch R = 1 ,5695.741,196.309900,196.309900,196.309900
XS GIS Cut Line= 2
1248108.51541265846056.1379021461247841.15430154845488.429568812
#Sta/Elev= 30
9500.368143.00499523.043132.18119530.776 127.0179548.428113.93319552.055112.1707
9570.187108.72719595.572100.0988 9607.7898.017059630.881 97.60699642.71698.66673
9675.35599.697239723.28599.898919744.257 100.7389787.775101.24339861.891104.8641
 9874.81103.7896 9936.46105.03679979.977104.28939994.48397.4962210001.7495.51802
10005.3695.4158110016.2496.57943 10031.395.61002 10062.1102.845310074.27107.2573
10085.14109.411710096.02113.0129 10106.9117.978110114.16122.313410127.88128.6969
#Mann= 3 , 0 , 0
9500.368    0.12       09500.368    0.12       010127.88    0.12       0
#XS Ineff= 2 , 0
       09950.215                       0
Bank Sta=9500.368,10127.88
Exp/Cntr=0.3,0.1

Type RM Length L Ch R = 1 ,5499.431,189.493800,189.493800,189.493800
XS GIS Cut Line= 6
1248238.60062045845867.7702100631248203.83570181845752.397110497
1248145.04639008845634.3422302431248085.87671539845553.972059247
1247976.67785365845432.5026212721247897.23069043845367.596235479
#Sta/Elev= 30
9499.146115.97829508.754111.43629525.683105.73619539.22699.243139546.95196.67218
9552.846 95.91439563.22695.767689580.52794.389889594.36795.348539601.28893.84412
9608.20893.414779632.85493.841389705.594 93.20829770.42897.370129798.30295.77713
9848.22897.654259870.50899.495759904.52698.992189947.085100.9968 9966.77100.9598
9974.11299.788359991.82891.667229999.85288.5044510003.8387.6436410007.8489.13847
10021.2596.9547910035.37104.140510056.56110.974310069.27116.625410117.78 141.827
#Mann= 3 , 0 , 0
9499.146    0.12       09499.146    0.12       010117.78    0.12       0
#XS Ineff= 2 , 0
       09954.639                       0
Bank Sta=9499.146,10117.78
Exp/Cntr=0.3,0.1

Type RM Length L Ch R = 1 ,5309.937,361.945000,361.945000,361.945000
XS GIS Cut Line= 6
1248328.63039344845791.6983273411248283.85266451845620.091872808
1248255.73835759845551.0299698971248200.89751179845444.101715395
1248090.44980874845256.5438729561247919.87247284845077.745251681
#Sta/Elev= 30
9521.575120.04139547.223106.03669557.27999.227799560.63197.715949570.68896.57982
9594.15390.598549614.44688.452179631.42682.764329639.33282.168819645.14682.44656
9662.38789.118519671.31890.369639719.93889.269879749.94190.165839771.19589.37426
9787.42290.002839796.63489.044079855.51789.272819889.05991.324959919.37291.59495
9938.37790.494339969.20486.4448110004.1884.90199 10023.5 86.8141 10046.590.86269
10065.1592.3857910147.0192.64086 10236.595.2495210309.05102.556210358.75111.8649
#Mann= 3 , 0 , 0
9521.575    0.12       09521.575    0.12       010358.75    0.12       0
#XS Ineff= 2 , 0
       09926.477                       0
Bank Sta=9521.575,10358.75
Exp/Cntr=0.3,0.1

Type RM Length L Ch R = 1 ,4947.992,303.051100,303.051100,303.051100
XS GIS Cut Line= 4
1248410.25152376845815.5129021461248444.10569043845544.679568812
1248467.54319043845161.867068812 1248431.0848571844758.221235478
#Sta/Elev= 30
9419.277124.46179465.269105.81549471.882102.29289485.10793.351229488.41391.62181
9508.252 90.84989521.47787.230319541.31584.86116 9564.4683.405079587.60482.75457
  9637.2 83.28049690.10284.875319759.14181.634319864.32479.620699880.75978.10795
9962.93378.644999972.79477.090959989.22973.2852610005.6671.6759810028.6773.50792
10048.39 74.243610077.9876.7674310097.7577.3784710189.98 84.118610308.5887.27481
10331.6388.9795710377.7596.42247 10407.498.9700410423.87102.063210481.04122.0357
#Mann= 3 , 0 , 0
9419.277    0.12       09419.277    0.12       010481.04    0.12       0
#XS Ineff= 2 , 0
       09836.679        10114.31       0
Bank Sta=9419.277,10481.04
Exp/Cntr=0.3,0.1

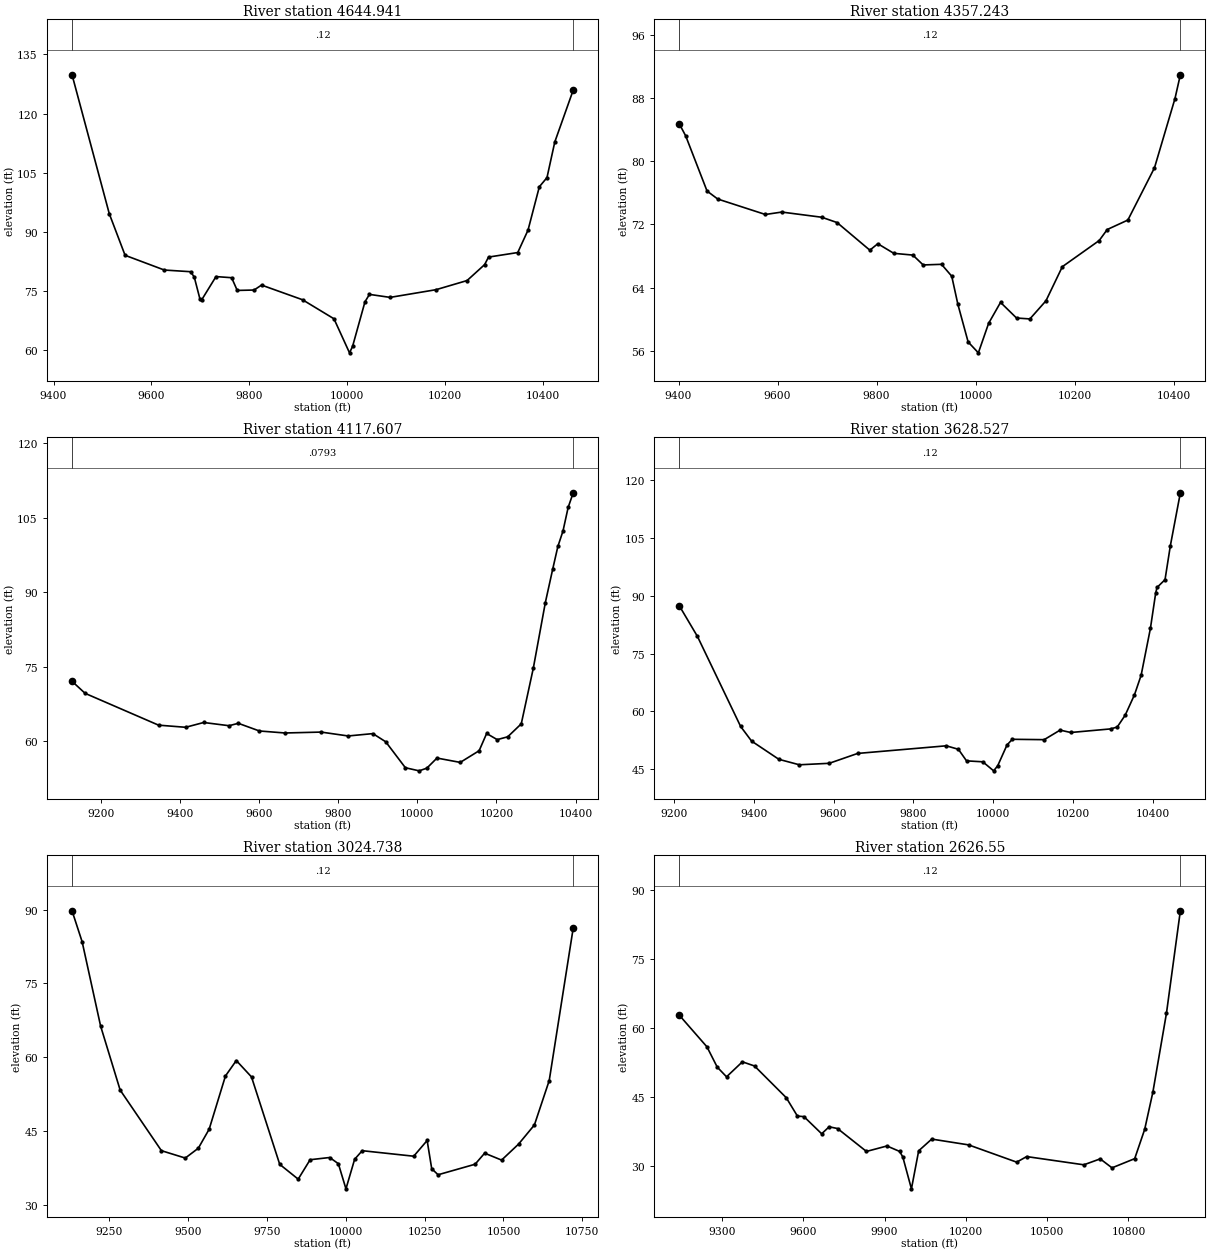
Type RM Length L Ch R = 1 ,4644.941,287.698400,287.698400,287.698400
XS GIS Cut Line= 6
1248437.16124598845843.2906799241248661.70291287845466.401066671
1248721.23828766845362.1976389871248784.05847679845258.816946517
1248834.73069043845182.700402145 1248977.9598571844974.367068812
#Sta/Elev= 30
9437.765129.84139513.91494.605649546.13484.093179626.33380.359129679.79879.93686
9687.43678.596239698.893 73.10089702.71272.820999731.857 78.69979763.81578.41494
9775.27275.191699809.64375.291029824.91976.54777 9908.6272.83229 9972.9168.00355
10004.6559.3755510010.8460.9832610036.2472.3104910045.3974.1884110087.6273.42799
10181.4275.3788110244.8477.6944210280.6881.7326410288.6483.6411410348.3684.79306
10369.3190.4577510392.48101.464810408.08103.776710424.01112.804410461.72125.9747
#Mann= 3 , 0 , 0
9437.765    0.12       09437.765    0.12       010461.72    0.12       0
#XS Ineff= 2 , 0
       09843.246        10134.54       0
Bank Sta=9437.765,10461.72
Exp/Cntr=0.3,0.1

Type RM Length L Ch R = 1 ,4357.243,239.636000,239.636000,239.636000
XS GIS Cut Line= 2
1248602.59635001845983.4897170811249218.91579443845180.538328186
#Sta/Elev= 30
9401.29184.765539414.51983.199789457.62576.225429479.17875.21431 9575.4573.25893
9608.53773.564689689.32272.908869720.20672.23674 9786.3868.742149802.47669.55754
9834.806  68.3429873.23468.120859894.07766.872429931.13666.951939951.81665.44506
9964.22361.879329984.90357.1259410005.5855.7490910026.2659.4803910050.3462.13349
10082.6760.1554310109.61   60.0410142.0762.3331510175.1566.65111 10249.669.96108
10265.8771.35641 10307.5  72.55410361.2779.1691710402.6387.9266910413.5190.93956
#Mann= 3 , 0 , 0
9401.291    0.12       09401.291    0.12       010413.51    0.12       0
#XS Ineff= 2 , 0
       09848.697        10181.42       0
Bank Sta=9401.291,10413.51
Exp/Cntr=0.3,0.1

Type RM Length L Ch R = 1 ,4117.607,489.079500,489.079500,489.079500
XS GIS Cut Line= 2
1248728.46440557846384.9654115141249368.46477613 845292.40526326
#Sta/Elev= 30
9127.85272.099389160.89369.674569346.40563.275439414.84762.844949460.47463.81077
9524.38763.163479547.927 63.64559601.15862.103629665.79761.699529757.05261.88146
9825.49361.099879887.88261.574119920.33759.93041 9969.9854.7078110004.72 54.0833
10024.1954.6215710049.8356.6546910108.5755.7815410156.2958.12626 10175.3 61.5991
10201.9260.3625310228.5460.9308410262.7663.5384710293.1774.7242610323.5987.93813
10342.2594.6830610355.2399.2278610368.21102.3417 10381.2107.084210394.06110.0286
#Mann= 3 , 0 , 0
9127.852  0.0793       09127.852  0.0793       010394.06  0.0793       0
#XS Ineff= 2 , 0
       09876.608        10171.46       0
Bank Sta=9127.852,10394.06
Exp/Cntr=0.3,0.1

Type RM Length L Ch R = 1 ,3628.527,603.788700,603.788700,603.788700
XS GIS Cut Line= 6
1249316.04639532846504.9372759071249431.43441988846112.424257654
1249457.49160723846009.6183973411249494.85834851845840.810521572
1249524.08666599845732.675486594 1249602.9598571845282.526791034
#Sta/Elev= 30
 9212.6487.445069258.52579.435489366.85656.111689394.244 52.33039462.71347.60419
9514.06546.184399589.07346.567819660.38449.128069882.645 51.1029 9913.0350.19631
9933.42847.201449974.22346.9571610001.4144.6168910011.5945.9276410034.9251.30945
10048.2552.7898710128.19 52.692810168.1655.16974 10194.854.5513510294.7355.48001
10311.3855.9627210331.3759.0361410354.6864.3195110371.3469.3758910394.6581.53062
10407.9890.7627810411.3192.1378910431.2994.1442710444.61 102.91310469.74116.6577
#Mann= 3 , 0 , 0
 9212.64    0.12       0 9212.64    0.12       010469.74    0.12       0
#XS Ineff= 2 , 0
       09878.101        10142.75       0
Bank Sta=9212.64,10469.74
Exp/Cntr=0.3,0.1

Type RM Length L Ch R = 1 ,3024.738,398.188300,398.188300,398.188300
XS GIS Cut Line= 3
1249756.96556294846673.1598559471250058.61486849845715.043536499
1250180.14264628845144.297008738
#Sta/Elev= 30
9133.04889.782429165.10983.467899223.58266.340359285.49553.331279416.19941.00807
 9491.8739.505139533.14541.505159567.54145.377579619.13556.195269653.53159.33374
9701.68555.999399791.11538.226999849.58835.218499887.42339.166319949.33639.61925
9976.85338.3614410000.9333.2473910028.4539.2617810052.5241.0039810215.6439.88055
10258.1943.0758310272.6637.3422410292.79 36.109310410.1938.2513210440.38 40.4986
10494.0539.0914710547.7242.3340110598.0446.23537   1064555.2684210721.0786.29436
#Mann= 3 , 0 , 0
9133.048    0.12       09133.048    0.12       010721.07    0.12       0
#XS Ineff= 2 , 0
       09760.166        10079.92       0
Bank Sta=9133.048,10721.07
Exp/Cntr=0.3,0.1

Type RM Length L Ch R = 1 , 2626.55,386.110900,386.110900,386.110900
XS GIS Cut Line= 3
1250017.81249195846933.9309913811250322.14388487845975.712554932
1250493.58485717845148.846235484
#Sta/Elev= 30
 9141.7262.922469244.31756.006769282.18251.603049316.60649.490569375.12552.75193
9419.87651.843979536.91544.955959578.22340.953619602.31940.833689667.72337.10751
9695.26238.625469726.243 38.24939832.95533.266929908.686 34.45559955.65233.26404
9967.206 32.05429999.00625.1361810025.73 33.405410073.9235.9532310209.89 34.6927
10387.4730.9384310424.3332.1502710635.4230.3606910695.7331.6515110739.2929.69992
10823.0531.6978210859.9138.0687710890.0746.1378910940.3363.3347510991.5685.58774
#Mann= 3 , 0 , 0
 9141.72    0.12       0 9141.72    0.12       010991.56    0.12       0
#XS Ineff= 2 , 0
       09897.548        10350.22       0
Bank Sta=9141.72,10991.56
Exp/Cntr=0.3,0.1

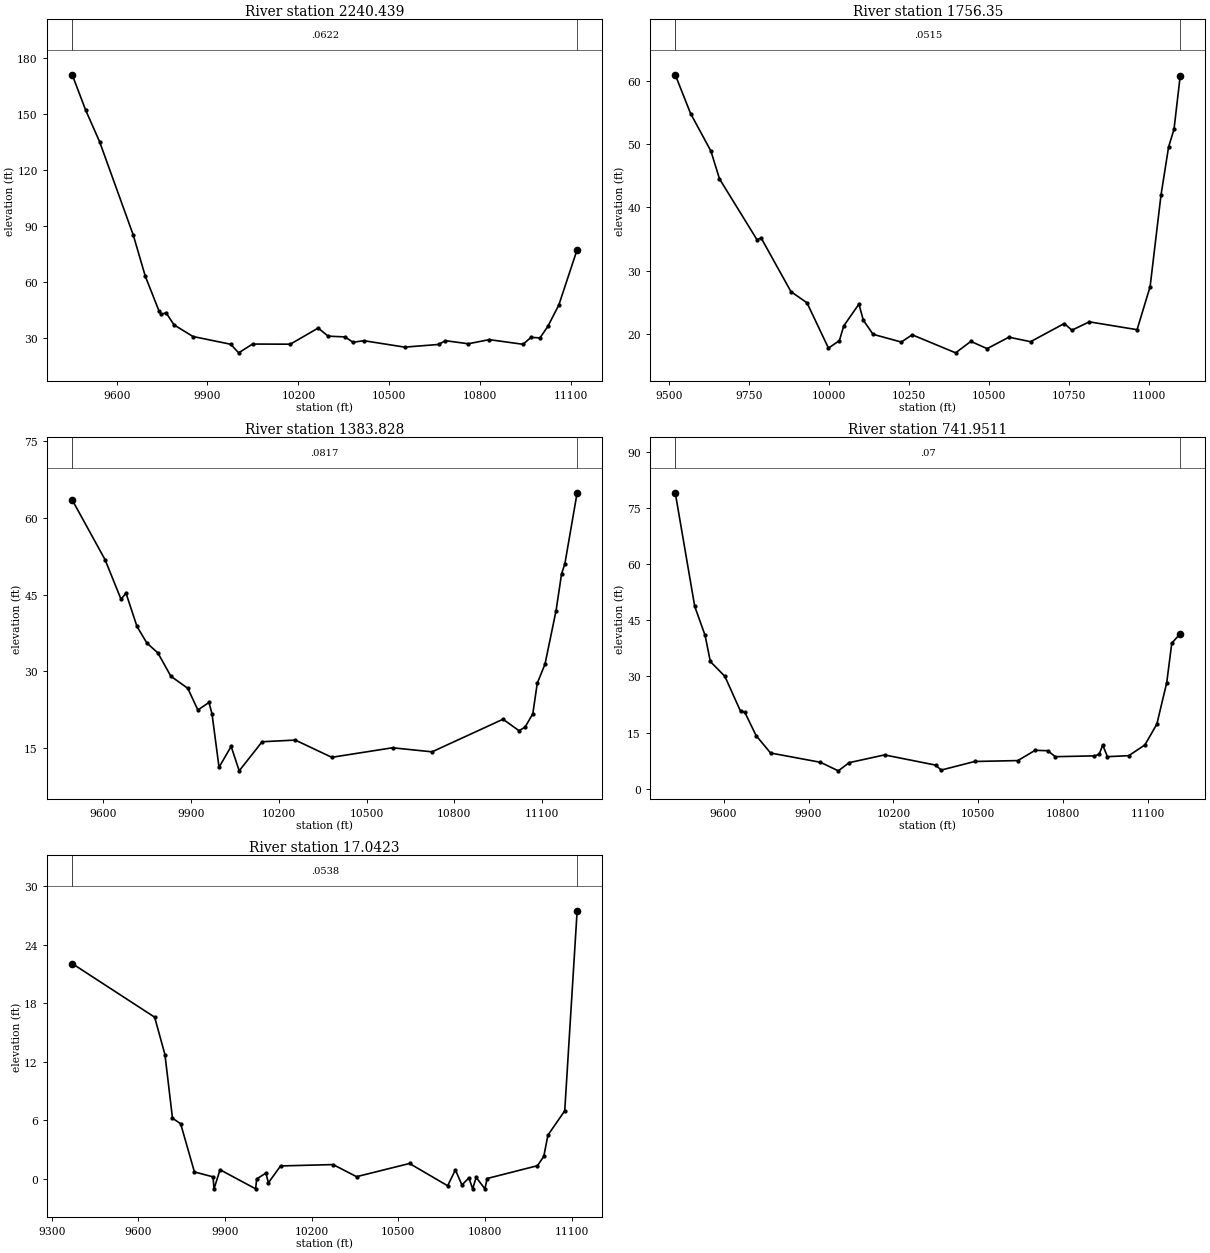
Type RM Length L Ch R = 1 ,2240.439,484.089300,484.089300,484.089300
XS GIS Cut Line= 5
1250620.81569206846827.9994002061250617.99990502 846620.86179186
1250616.85782084846201.161927171 1250615.0900448846117.303216704
1250570.88520432845161.686223905
#Sta/Elev= 30
9453.322171.10779497.671152.19719543.607135.30589655.16685.170759694.53663.29971
9740.46844.41253 9747.0342.945399763.43443.629319789.68137.177759852.01730.98321
9976.68926.8307410002.94 22.235910048.8726.9420710173.5726.8684210265.5335.50497
10298.3731.1642410354.2130.7687310380.4827.8905510416.6128.7341310551.2725.28629
10662.9326.7223410685.9328.7328310761.4727.0936810830.4429.30235 10942.126.80927
10968.3830.5198510997.9430.2486211024.21 36.452611060.3447.90674 11120.777.48444
#Mann= 3 , 0 , 0
9453.322  0.0622       09453.322  0.0622       0 11120.7  0.0622       0
#XS Ineff= 2 , 0
       09908.034        10646.98       0
Bank Sta=9453.322,11120.7
Exp/Cntr=0.3,0.1

Type RM Length L Ch R = 1 , 1756.35,372.521600,372.521600,372.521600
XS GIS Cut Line= 6
1251162.42166266846702.7090827031251120.40720202846488.145346511
1251089.84861911846304.9684722521251077.83013424846244.419759639
1251067.93004335846210.1439629431250793.58980628845170.597819547
#Sta/Elev= 30
9519.413  61.0019567.31354.866299630.83348.922249657.57844.529449774.40234.92212
9787.70735.17202 9880.8426.677329930.77224.919049997.92417.74394   1003218.93016
10045.5821.2575110093.0824.7090810106.65 22.177310137.19 19.932210225.4118.70425
10259.3519.8537910395.0716.9984710442.5818.8094510493.4717.6622810561.3419.47465
 10629.218.7650310734.3921.6373510758.1420.5825510812.4321.9040810961.7320.66143
11002.45 27.485611036.3841.9441811060.13 49.5725 11077.152.39418 11096.360.77149
#Mann= 3 , 0 , 0
9519.413  0.0515       09519.413  0.0515       0 11096.3  0.0515       0
#XS Ineff= 2 , 0
       0                10745.58       0
Bank Sta=9519.413,11096.3
Exp/Cntr=0.3,0.1

Type RM Length L Ch R = 1 ,1383.828,641.877200,641.877200,641.877200
XS GIS Cut Line= 4
1251547.83832932846681.8757493691251443.67166266846310.347971591
1251383.98594171846124.9688161191250815.19944043845129.792416034
#Sta/Elev= 30
9493.52163.448329606.016 51.78299660.40644.089129677.44245.276629714.92338.79174
9748.99735.531479786.47733.629659830.77329.081589888.80526.717079923.27222.49112
9961.18623.960339971.52621.759189995.65311.3183610037.0115.3987110064.5910.62801
10143.0216.3010510256.39 16.627810381.0913.2670810588.9315.1268110724.1514.33396
10966.8220.6887311021.6818.45544 11042.419.1584411068.8521.7750611083.9727.71139
11110.4231.4196511148.21 41.847211167.1449.0389311178.4451.0163511220.3864.85005
#Mann= 3 , 0 , 0
9493.521  0.0817       09493.521  0.0817       011220.38  0.0817       0
#XS Ineff= 2 , 0
       0                10821.13       0
Bank Sta=9493.521,11220.38
Exp/Cntr=0.3,0.1

Type RM Length L Ch R = 1 ,741.9511,724.908800,724.908800,724.908800
XS GIS Cut Line= 6
1252040.89388488846306.8757493691251817.56379648845865.659416714
1251767.87647759845732.105787172    1251718.9932845640.474467449
1251529.67715714845385.3359061451251079.08832932844817.292416033
#Sta/Elev= 30
9429.138 79.03799497.84348.724929534.62840.92521 9553.0233.974269604.51930.00235
9659.69620.68962 9674.4120.471699714.80714.179549765.9439.5294049942.1327.053206
10005.244.76878310043.566.95158910168.539.02193310349.046.30104210368.69 4.96664
10487.137.268482 10639.67.50923210700.6810.2501210745.1910.1435910771.878.549558
10910.068.76536210926.819.18645310939.3711.6627310956.128.552205 11031.58.826473
11088.3411.6805711130.5817.2437111165.5128.3095611183.3738.8527511213.03 41.3975
#Mann= 3 , 0 , 0
9429.138    0.07       09429.138    0.07       011213.03    0.07       0
#XS Ineff= 2 , 0
       09783.033        10603.09       0
Bank Sta=9429.138,11213.03
Exp/Cntr=0.3,0.1

Type RM Length L Ch R = 1 , 17.0423,0.000000,0.000000,0.000000
XS GIS Cut Line= 6
1252564.40190557845844.6008281861252286.62412778845525.590411499
1252206.32898885845310.7466615141252115.18315557845208.750133738
1251705.02690557845022.1181892751251470.65190557844572.899439275
#Sta/Elev= 30
9371.27922.060049656.582 16.57559692.22612.747419718.3286.2313799746.5115.671529
9794.2780.7305459858.6240.2271529862.095  -0.9999882.9170.95702910006.18  -0.999
10009.740.01786910041.590.60852410050.39-0.37791 10092.5 1.3464210274.271.484231
10355.530.24655710538.88   1.59710670.81-0.68418 10697.60.93911310720.32-0.60594
 10744.3 0.1230110757.44  -0.99910769.550.17755610799.85  -0.99910807.420.058069
10981.751.37043611003.522.31895111018.044.505091 11076.16.98701211119.0627.46877
#Mann= 3 , 0 , 0
9371.279  0.0538       09371.279  0.0538       011119.06  0.0538       0
#XS Ineff= 2 , 0
       09915.573        10645.45       0
Bank Sta=9371.279,11119.06
Exp/Cntr=0.3,0.1